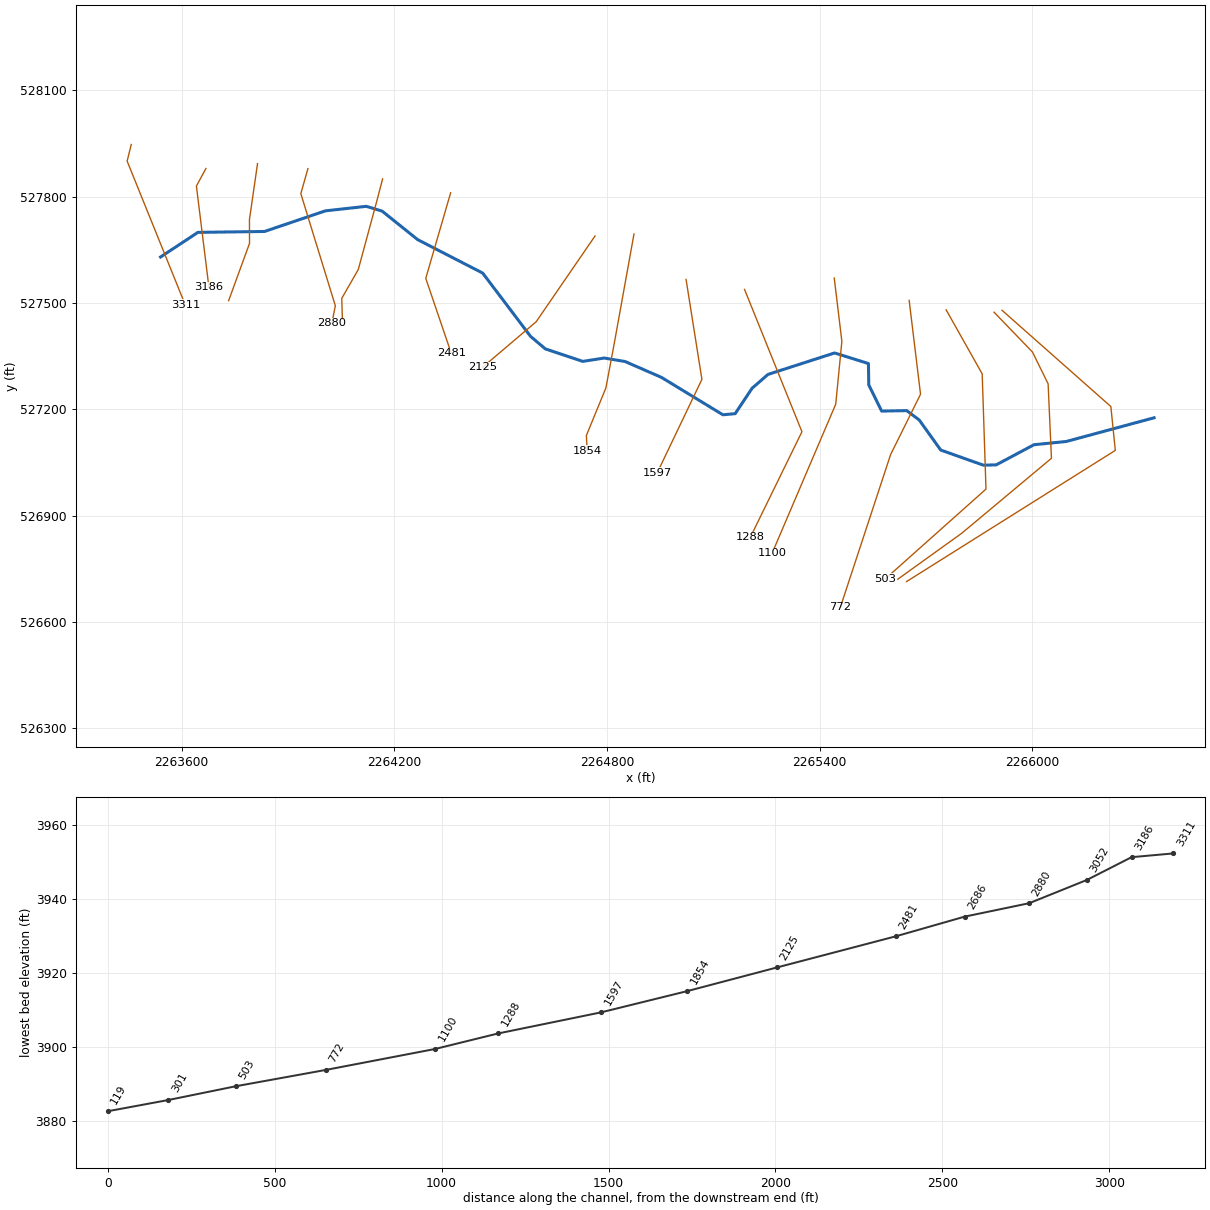
--- BLKRN.prj (project) ---

Proj Title=BLKRN
Current Plan=p01
Default Exp/Contr=0,0
English Units
Geom File=g01
Flow File=f01
Plan File=p01
Background Map Layer=Inundation Boundary (01pct Value_0)
BEGIN DESCRIPTION:
----------MODEL BY WOOD PLC 2021----------
Stream Name: Black Run
Flood Zone: Enhanced Approximate
Pocahontas County, WV
HEC-RAS Version: RAS 6.0
Vertical Datum: NAVD88
Projection: NAD 1983 StatePlane West Virginia S FIPS 4702 (US Feet)
Terrain: 1-meter LIDAR (FEMA Region III 3DEP collected 2016-2018)
Land Use: 2016 NLCD
Hydrologic Method:
WV SIR2010-5033 regression equations
END DESCRIPTION:
DSS Export Rating Curves= 0
DSS Export Rating Curve Sorted= 0
DSS Export Volume Flow Curves= 0
DXF OffsetX= 0
DXF OffsetY= 0
DXF ScaleX= 0
DXF ScaleY= 0

--- BLKRN.p01 (plan) ---

Plan Title=Floodplain
Program Version=6.10
Short Identifier=Floodplain
Geom File=g01
Flow File=f01
Subcritical Flow
K Sum by GR= 0
Std Step Tol= 0.01
Critical Tol= 0.01
Num of Std Step Trials= 20
Max Error Tol= 0.3
Flow Tol Ratio= 0.001
Split Flow NTrial= 30
Split Flow Tol= 0.02
Split Flow Ratio= 0.02
Log Output Level= 0
Friction Slope Method= 1
Unsteady Friction Slope Method= 2
Unsteady Bridges Friction Slope Method= 1
Parabolic Critical Depth
Global Vel Dist= 0 , 0 , 0
Global Log Level= 0
CheckData=True
Encroach Param=-1 ,0,0, 0
Mapping Interval=1HOUR
Computation Time Step Use Courant=        0
Computation Time Step Use Time Series=    0
Computation Time Step Count To Double=0
Computation Time Step Max Doubling=0
Computation Time Step Max Halving=0
Computation Time Step Residence Courant=0
Run HTab= 0
Run UNet= 0
Run Sediment= 0
Run PostProcess= 0
Run WQNet= 0
Run RASMapper=-1
UNET Theta= 0
UNET Theta Warmup= 0
UNET ZTol= 0
UNET ZSATol= 0
UNET MxIter= 0
UNET Max Iter WO Improvement= 0
UNET MaxInSteps= 0
UNET DtIC= 0
UNET DtMin= 0
UNET MaxCRTS= 0
UNET WFStab= 0
UNET SFStab= 0
UNET WFX= 1
UNET SFX= 1
UNET Gravity=32.174
UNET 1D Methodology=Finite Difference
UNET DSS MLevel= 1
UNET Pardiso=0
UNET DZMax Abort= 0
UNET Use Existing IB Tables= 0
UNET Froude Reduction=False
UNET Froude Limit= 0
UNET Froude Power= 0
UNET D1 Cores= 0
UNET WindReference=Eulerian
UNET WindDragFormulation=Hsu (1988)
UNET D2 Coriolis=0
UNET D2 Cores= 0
UNET D2 Theta= 1
UNET D2 Theta Warmup= 1
UNET D2 Z Tol= 0.01
UNET D2 Volume Tol= 0.01
UNET D2 Max Iterations= 20
UNET D2 Equation= 0
UNET D2 RampUpFraction=0.1
UNET D2 TimeSlices= 1
UNET D2 Turbulence Formulation=Non-Conservative (original)
UNET D2 Eddy Viscosity=0.3
UNET D2 Transverse Eddy Viscosity=0.1
UNET D2 Smagorinsky Mixing=0
UNET D2 BCVolumeCheck=0
UNET D2 Cores=0
UNET D2 SolverType=PARDISO (Direct)
UNET D2 Minimum Iterations= 2147483647
UNET D2 Maximum Iterations= 2147483647
UNET D2 Restart Number= 10
UNET D2 Relaxation Coeff=1.3
UNET D2 SOR Precondition Iterations= 10
UNET D2 ILUT Maximum Fill= 8
UNET D2 ILUT Tolerance=1E-08
UNET D1D2 MaxIter= 0
UNET D1D2 ZTol=0.01
UNET D1D2 QTol=0.1
UNET D1D2 MinQTol=1
Write IC File= 0
Write IC File at Fixed DateTime=0
Write IC File at Sim End=0
Echo Input=False
Echo Parameters=False
Echo Output=False
Write Detailed= 0
HDF Write Warmup=0
HDF Write Time Slices=0
HDF Flush=0
HDF Compression= 1
HDF Chunk Size= 1
HDF Spatial Parts= 1
HDF Use Max Rows=0
HDF Fixed Rows= 1
Calibration Method= 0
Calibration Iterations= 20
Calibration Max Change=0.05
Calibration Tolerance=0.2
Calibration Maximum=1.5
Calibration Minimum=0.5
Calibration Optimization Method= 1
WQ AD Non Conservative
WQ ULTIMATE=-1
WQ Max Comp Step=1HOUR
WQ Output Interval=15MIN
WQ Output Selected Increments= 0
WQ Output face flow=0
WQ Output face velocity=0
WQ Output face area=0
WQ Output face dispersion=0
WQ Output cell volume=0
WQ Output cell surface area=0
WQ Output cell continuity=0
WQ Output cumulative cell continuity=0
WQ Output face conc=0
WQ Output face dconc_dx=0
WQ Output face courant=0
WQ Output face peclet=0
WQ Output face adv mass=0
WQ Output face disp mass=0
WQ Output cell mass=0
WQ Output cell source sink temp=0
WQ Output nsm pathways=0
WQ Output nsm derived pathways=0
WQ Create Restart=0
WQ Fixed Restart=0
WQ System Summary=0
WQ Write To DSS=0
Sorting and Armoring Iterations= 10
XS Update Threshold= 0.02
Bed Roughness Predictor= 0
Hydraulics Update Threshold= 0.02
Energy Slope Method= 1
Volume Change Method= 1
Sediment Retention Method= 0
Sediment TS Multiplier= 1
Warm Up Method= 0
XS Weighting Method= 0
Number of US Weighted Cross Sections= 1
Number of DS Weighted Cross Sections= 1
Upstream XS Weight=0
Main XS Weight=1
Downstream XS Weight=0
Number of DS XS's Weighted with US Boundary= 1
Upstream Boundary Weight= 1
Weight of XSs Associated with US Boundary= 0
Number of US XS's Weighted with DS Boundary= 1
Downstream Boundary Weight= 0.5
Weight of XSs Associated with DS Boundary= 0.5
Percentile Method= 0
Sediment Output Level= 3
Mass or Volume Output= 0
Output Increment Type= 1
Profile and TS Output Increment= 1
Transport Output Increment 1
XS Output Flag= 0
XS Output Increment= 10
Read HDF5 Sediment Hotstart= 0
Sediment Hotstart Type= 0
Write Gradation File= 0
Read Gradation Hotstart= 0
Write HDF5 File= 1
Write Binary Output= 1
Write DSS Sediment File= 0
DSS Sediment Output Type= 1
SV Curve= 0
Specific Gage Flag= 0
Subcell Erosion Methods= 0
Subcell Deposition Methods= 0
Advection Scheme= 1
Matrix Solver= 0
Implicit Weighting Factor= 1
Maximum Outer Loop Convergence Iterations= 5
Convergence Maximum Absolute= 0.001
Convergence RMSE= 0.0001
Grain Fractions Max Abs Error= 0.001
Max Subgrid Regions= 1
Max Subgrid Length Scale= 3.402823E+38
Initial Layer Thickness= 3.402823E+38
Min Layer Thickness= 3.402823E+38
Max Layer Thickness= 3.402823E+38
Number of Layers= 5

--- BLKRN.f01 (steady flow) ---

Flow Title=Flow
Program Version=6.10
Number of Profiles= 6
Profile Names=01pct,10pct,04pct,02pct,0_2pct,01plus
River Rch & RM=BLKRN,Main            ,3311
     568     300     399     480     793     839
Boundary for River Rch & Prof#=BLKRN,Main            , 1
Up Type= 0
Dn Type= 3
Dn Slope=0.01896
Boundary for River Rch & Prof#=BLKRN,Main            , 2
Up Type= 0
Dn Type= 3
Dn Slope=0.01896
Boundary for River Rch & Prof#=BLKRN,Main            , 3
Up Type= 0
Dn Type= 3
Dn Slope=0.01896
Boundary for River Rch & Prof#=BLKRN,Main            , 4
Up Type= 0
Dn Type= 3
Dn Slope=0.01896
Boundary for River Rch & Prof#=BLKRN,Main            , 5
Up Type= 0
Dn Type= 3
Dn Slope=0.01896
Boundary for River Rch & Prof#=BLKRN,Main            , 6
Up Type= 0
Dn Type= 3
Dn Slope=0.01896
DSS Import GetInterval= 0
DSS Import GetPeak= 0
DSS Import FillOption= 0

--- BLKRN.g01 (geometry) ---

Geom Title=Geometry
Program Version=6.10

River Reach=BLKRN           ,Main
Reach XY= 30
     2263540.243      527630.005     2263645.772       527699.55
     2263833.736      527702.073     2264005.533      527760.286
     2264120.984      527773.021     2264165.738      527759.377
     2264265.669      527679.124      2264449.23      527584.711
     2264584.425      527405.983      2264625.91      527370.899
     2264731.551      527335.501     2264792.295      527344.991
     2264851.399      527335.037     2264953.832      527290.287
     2265127.099      527184.828     2265161.643         527188.
     2265209.467      527259.817     2265254.496      527298.797
      2265442.24      527359.292     2265537.718      527329.462
     2265538.609      527269.338     2265574.971      527195.302
     2265645.677      527196.592     2265680.797      527170.412
      2265741.71      527085.344     2265862.023      527042.643
     2265898.157      527043.507     2266004.732      527100.333
     2266096.222      527109.556     2266343.667      527176.369

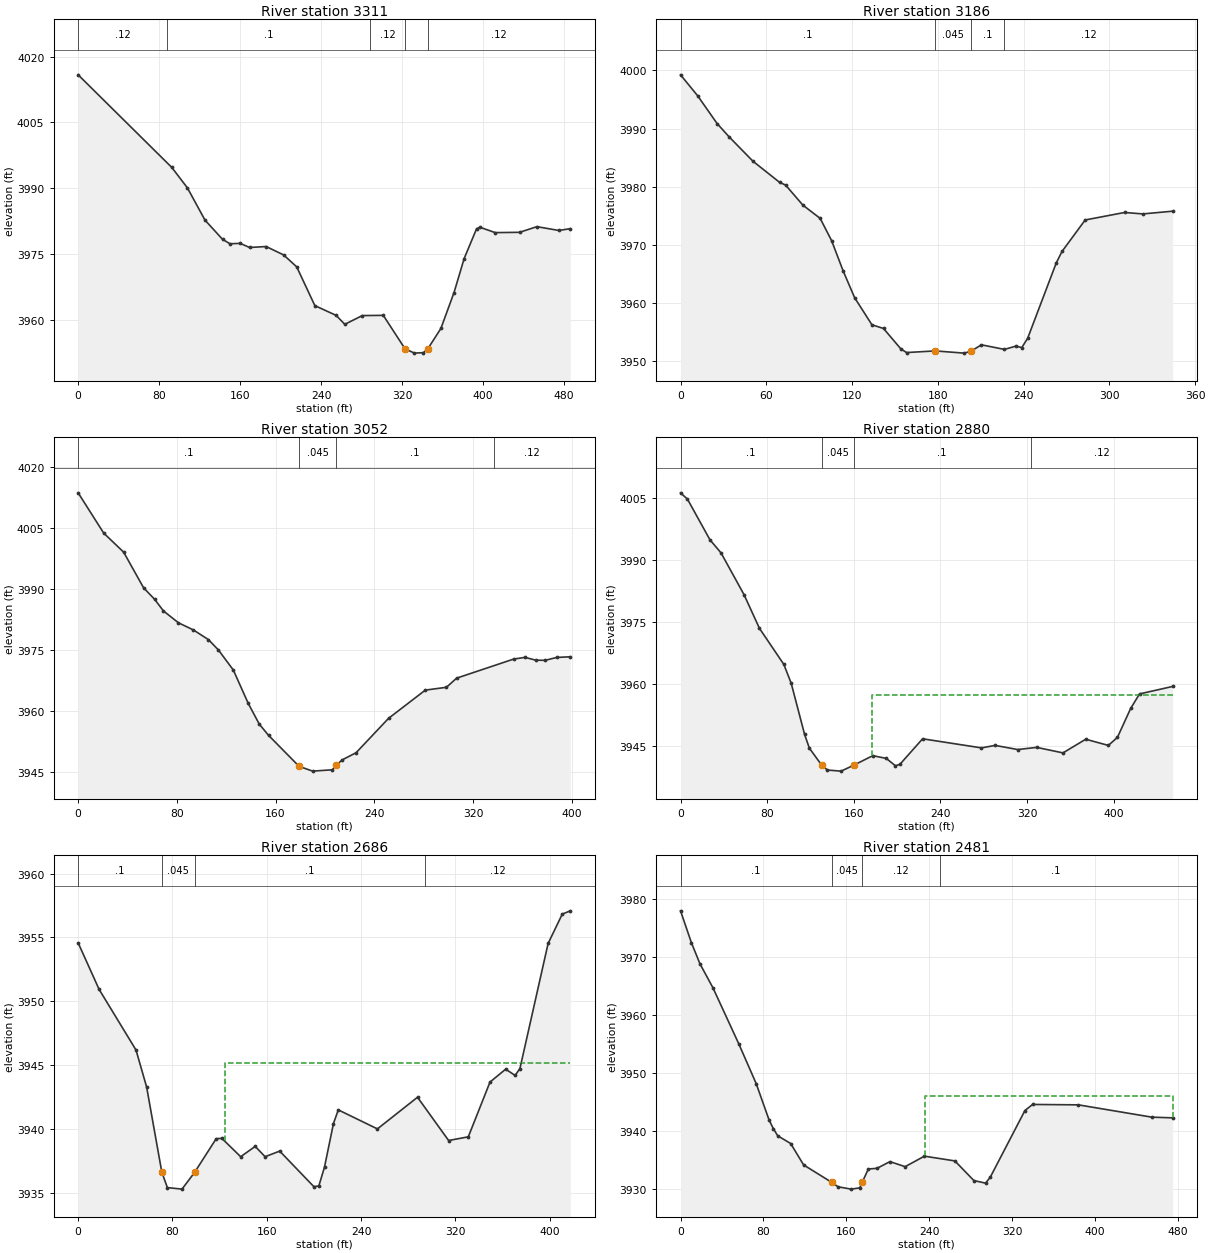
Type RM Length L Ch R = 1 ,3311    ,130.1,125.3,118.7
XS GIS Cut Line= 3
2263457.65475374527947.4868158972263446.04741633527900.656232748
2263610.11876555527494.682166817
#Sta/Elev= 30
       0 4015.85    92.5 3994.74   107.9 3990.09   125.3 3982.73   142.6 3978.36
     150 3977.34   160.1 3977.43   169.3 3976.49   185.7 3976.71     203 3974.79
   215.9 3972.07   233.8 3963.24   254.8 3961.02   263.4 3958.98   280.7 3960.97
   301.4 3961.02   322.9 3953.39   332.2 3952.41   341.1 3952.52   345.4  3953.4
   358.3 3958.03   371.3 3966.23   381.3 3973.98   393.6 3980.79   397.1 3981.08
     412 3979.88     436 3979.95   453.2 3981.24   474.8 3980.37   486.1 3980.78
#Mann= 5 ,-1,0
       0     .12       0   88.25      .1       0  288.25     .12       0
   322.9    .045       0   345.4     .12       0
Bank Sta=322.9,345.4
XS Rating Curve= 0 ,0
Exp/Cntr=0.3,0.1

Type RM Length L Ch R = 1 ,3186    ,136.3,134.2,131.7
XS GIS Cut Line= 3
 2263668.3558062527879.7012351642263641.47572503527830.185296171
2263676.84425288527544.407591125
#Sta/Elev= 30
       0 3999.23      12 3995.62    25.6 3990.85    33.9 3988.59    50.7 3984.37
    69.4 3980.73    73.5 3980.28    85.6 3976.83    97.7 3974.55   105.7 3970.72
   113.8  3965.5   121.8 3960.92   133.9 3956.26     142 3955.63   154.1 3952.13
   158.1 3951.49   178.3 3951.77   198.4 3951.39   203.1 3951.71   210.5 3952.82
   226.6 3952.03   234.7  3952.6   238.7 3952.34   242.8 3953.91   262.9 3966.92
   266.9 3968.87   283.1 3974.28   310.7 3975.57   323.4 3975.32   344.3 3975.79
#Mann= 4 ,-1,0
       0      .1       0   178.3    .045       0   203.1      .1       0
   226.6     .12       0
Bank Sta=178.3,203.1
XS Rating Curve= 0 ,0
Exp/Cntr(USF)=0,0
Exp/Cntr=0.3,0.1

Type RM Length L Ch R = 1 ,3052    ,166.1,172.4,177.9
XS GIS Cut Line= 4
2263813.97111614527893.6754054382263791.17370736527735.783486047
2263791.35131696527668.4788451682263732.44544939527506.794434311
#Sta/Elev= 30
       0 4013.54    20.7 4003.66    36.9 3998.97      53 3990.24    62.1 3987.36
    69.1 3984.55    81.3 3981.63    93.5 3979.86   105.6  3977.5   113.7 3974.96
   125.8 3970.02   137.9 3961.82   146.8 3956.76   154.3 3954.01   179.1 3946.38
   190.1 3945.21   206.1 3945.54   209.3  3946.7   214.1 3947.98   225.3 3949.73
   251.6 3958.17   281.4  3965.1   298.5 3965.79   306.8 3968.04     353 3972.72
   362.3 3973.14   370.8 3972.46   378.5 3972.41   387.9 3973.12   398.9 3973.29
#Mann= 4 ,-1,0
       0      .1       0   179.1    .045       0   209.3      .1       0
  336.83     .12       0
Bank Sta=179.1,209.3
XS Rating Curve= 0 ,0
Exp/Cntr(USF)=0,0
Exp/Cntr=0.3,0.1

Type RM Length L Ch R = 1 ,2880    ,204,193.7,182.5
XS GIS Cut Line= 4
2263956.13031403 527879.345669142263936.15463216527808.756190151
2264033.56738071527492.3370097442264023.55983118527443.213919081
#Sta/Elev= 30
       0 4006.22     6.4 4004.69    27.2 3994.85    37.4  3991.7    58.6 3981.62
    72.9 3973.45    95.4 3964.74   102.2 3960.19   114.6 3947.79     119 3944.48
   130.63940.286   135.7 3939.18   148.3 3938.92     160 3940.35   177.6 3942.66
   190.1 3941.99   198.5 3940.21   202.7 3940.58   223.6 3946.74     278 3944.54
   290.6 3945.14   311.5 3944.14     329 3944.66   353.3 3943.33   374.3 3946.63
   395.2 3945.14   403.6 3947.09   415.8 3954.08     424 3957.59   454.6  3959.4
#Mann= 4 ,-1,0
       0      .1       0   130.6    .045       0     160      .1       0
  323.36     .12       0
#XS Ineff= 2 , 0
                          177.29         3957.38
Permanent Ineff=
       F       F
Bank Sta=130.6,160
XS Rating Curve= 0 ,0
Exp/Cntr(USF)=0,0
Exp/Cntr=0.3,0.1

Type RM Length L Ch R = 1 ,2686    ,203.5,205,203.3
XS GIS Cut Line= 5
2264166.87967292527850.3902727032264150.32183525527787.136117057
2264098.28463563527594.797038091 2264051.6112356527513.276743014
2264053.34959206 527454.34363737
#Sta/Elev= 30
       0 3954.57    17.8 3950.92    49.1 3946.17    58.1 3943.27   70.98  3936.6
    75.7 3935.39    88.1 3935.27   98.77 3936.58   117.1 3939.22   121.9 3939.25
   137.9 3937.81   150.2 3938.62   158.6 3937.81     171 3938.25     200 3935.46
   204.2 3935.52     209    3937   216.6 3940.41   220.7 3941.48   253.9 3939.99
   287.9 3942.47   314.3 3939.08     331 3939.37   349.4 3943.66   362.7 3944.67
   370.7 3944.18   374.8 3944.72   398.7 3954.52   410.7 3956.82   417.5 3957.08
#Mann= 4 ,-1,0
       0      .1       0   70.98    .045       0   98.77      .1       0
  294.64     .12       0
#XS Ineff= 2 , 0
                          124.64         3945.19
Permanent Ineff=
       F       F
Bank Sta=70.98,98.77
XS Rating Curve= 0 ,0
Exp/Cntr(USF)=0,0
Exp/Cntr=0.3,0.1

Type RM Length L Ch R = 1 ,2481    ,369.6,356.3,347.1
XS GIS Cut Line= 3
2264358.89402931527811.2437825552264288.64871645527569.775519583
2264360.65016213527358.161514579
#Sta/Elev= 30
       0 3977.92    10.5 3972.42    18.8 3968.77    31.3 3964.65    56.3 3954.97
      73 3948.16    85.5 3941.86    89.6 3940.39    93.8 3939.16   106.3 3937.83
   118.8 3934.14   145.9 3931.14   152.1 3930.37   164.6 3929.97   172.9 3930.18
   175.3 3931.14   181.3 3933.44   189.6 3933.55   202.1 3934.71   216.8 3933.84
   235.4 3935.65   264.8 3934.83   283.1 3931.45   294.4    3931   298.9 3932.01
   332.4 3943.51   339.8 3944.56     384 3944.49   454.9 3942.37     475 3942.25
#Mann= 4 ,-1,0
       0      .1       0   145.9    .045       0   175.3     .12       0
     250      .1       0
#XS Ineff= 2 , 0
                          236.23         3946.05
Permanent Ineff=
       F       F
Bank Sta=145.9,175.3
XS Rating Curve= 0 ,0
Exp/Cntr(USF)=0,0
Exp/Cntr=0.3,0.1

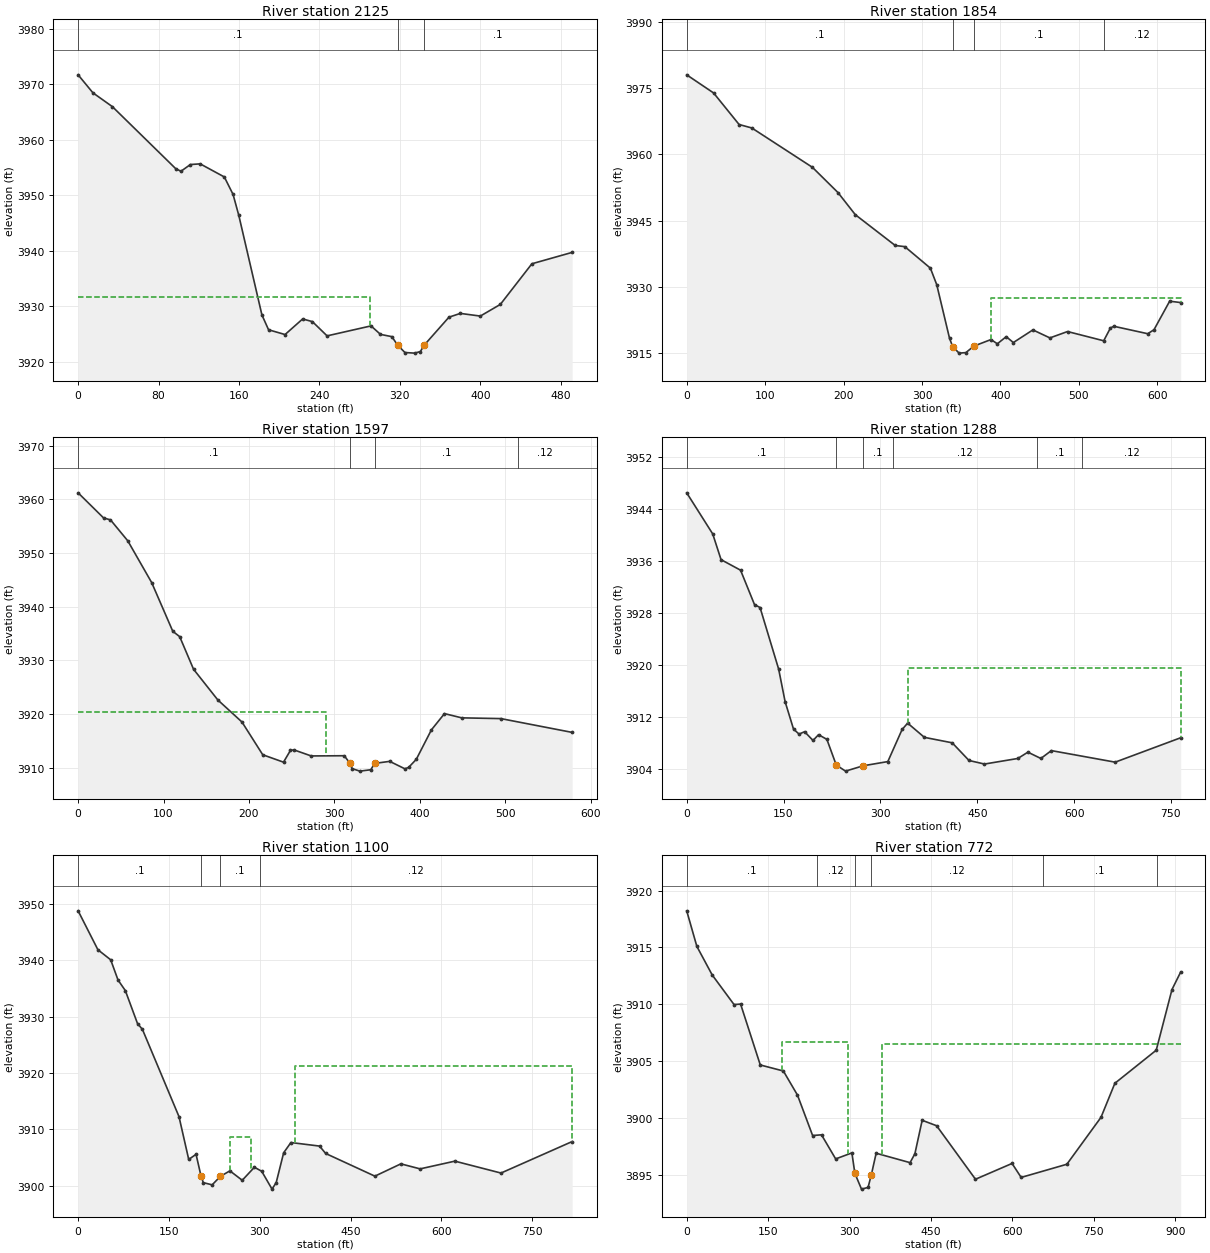
Type RM Length L Ch R = 1 ,2125    ,256.7,270.4,281.8
XS GIS Cut Line= 3
 2264766.2551986527689.301340147 2264600.1368135527447.310730042
2264449.35524944527319.288647347
#Sta/Elev= 30
       0 3971.69    14.7 3968.45    34.1 3965.95    97.2 3954.75   102.3 3954.31
   111.7 3955.52   121.4 3955.64   145.4 3953.28   154.1 3950.13   159.8 3946.35
   182.8  3928.4   189.4 3925.73   205.8 3924.87   223.3 3927.68     233  3927.2
   247.6 3924.63   291.3 3926.43   300.7  3924.9     312 3924.49   317.7 3922.98
     325 3921.63   334.7 3921.52   340.4 3921.81   344.2 3922.96   368.8    3928
   380.1 3928.68     400  3928.2   419.9  3930.3   451.3 3937.63   491.3 3939.68
#Mann= 3 ,-1,0
       0      .1       0   317.7    .045       0   344.2      .1       0
#XS Ineff= 2 , 0
          290.77 3931.69
Permanent Ineff=
       F       F
Bank Sta=317.7,344.2
XS Rating Curve= 0 ,0
Exp/Cntr(USF)=0,0
Exp/Cntr=0.3,0.1

Type RM Length L Ch R = 1 ,1854    ,263.2,257.4,253.6
XS GIS Cut Line= 5
2264876.20108039 527694.898397582264820.41553739527385.652321836
2264796.94343899527260.6606469352264741.80224219527126.307993039
2264744.13913677527083.074680096
#Sta/Elev= 30
       0 3977.98    34.3 3973.88    66.8 3966.75      83 3965.97   160.3 3957.07
   192.8 3951.38     215 3946.36   265.9  3939.4   278.1 3939.14   310.7 3934.28
   318.8 3930.55   335.1 3918.44   339.13916.556   347.3 3915.07     356 3915.19
   366.2 3916.66     388 3918.14   396.1 3917.18   407.4 3918.79   416.5 3917.46
   441.4 3920.32   463.1 3918.51   485.6 3919.95   531.7 3917.86   540.3 3920.76
   544.6 3921.14   587.8 3919.46   595.8 3920.35   615.8 3926.81   629.9  3926.5
#Mann= 4 ,-1,0
       0      .1       0   339.1    .045       0   366.2      .1       0
   531.7     .12       0
#XS Ineff= 2 , 0
       0                     388       0 3927.44
Permanent Ineff=
       F       F
Bank Sta=339.1,366.2
XS Rating Curve= 0 ,0
Exp/Cntr=0.3,0.1

Type RM Length L Ch R = 1 ,1597    ,283.5,308.4,316.5
XS GIS Cut Line= 3
2265023.15403803527566.6253439122265067.82688789527284.817015726
2264941.51701463527020.594105368
#Sta/Elev= 30
       0  3961.2    29.8 3956.52    37.9 3956.16    58.1 3952.26    86.1 3944.47
   110.8  3935.4   118.9 3934.39   135.1 3928.32   163.5  3922.6   191.8 3918.48
   216.1 3912.38   240.4    3911   248.5 3913.19   252.6 3913.29   272.8 3912.16
   311.5  3912.2   317.8 3910.88   320.8 3909.79   329.8 3909.33   342.6 3909.59
     347 3910.77   364.7 3911.15   382.5 3909.76   386.8 3910.02   395.8 3911.53
   413.5 3917.02   428.8 3920.05     449 3919.26   494.8 3919.12   578.2 3916.55
#Mann= 4 ,-1,0
       0      .1       0   317.8    .045       0     347      .1       0
  515.33     .12       0
#XS Ineff= 2 , 0
          290.39  3920.4
Permanent Ineff=
       F       F
Bank Sta=317.8,347
XS Rating Curve= 0 ,0
Exp/Cntr(USF)=0,0
Exp/Cntr=0.3,0.1

Type RM Length L Ch R = 1 ,1288    ,196.1,188.6,174.7
XS GIS Cut Line= 3
2265188.15599417527538.5361606732265350.09172913 527137.04260292
2265204.21573648526838.599058323
#Sta/Elev= 30
       0 3946.46    40.3 3940.13    53.2 3936.17    83.4 3934.55     105 3929.25
   113.6  3928.8   142.4 3919.32   152.4 3914.31   165.4 3910.09     174 3909.31
   182.6 3909.68   195.6 3908.33   204.2 3909.22   217.1  3908.5   231.6 3904.55
     246 3903.61   273.2 3904.43   311.5 3905.08   333.6 3910.02   342.2    3911
   368.1 3908.81   411.2 3907.97   437.2 3905.25   461.2  3904.7   512.9 3905.56
   528.4 3906.53   548.5 3905.56   564.8 3906.77   663.6 3904.99   765.1 3908.75
#Mann= 6 ,-1,0
       0      .1       0   231.6    .045       0   273.2      .1       0
     320     .12       0  542.92      .1       0  612.92     .12       0
#XS Ineff= 2 , 0
                          343.19         3919.52
Permanent Ineff=
       F       F
Bank Sta=231.6,273.2
XS Rating Curve= 0 ,0
Exp/Cntr(USF)=0,0
Exp/Cntr=0.3,0.1

Type RM Length L Ch R = 1 ,1100    ,322.8,328,304.4
XS GIS Cut Line= 4
2265441.23369701527570.6038796352265462.75233081527392.028775323
2265445.42811422527214.7585064132265265.60230107526793.498622419
#Sta/Elev= 30
       0 3948.74    32.7 3941.84    53.8 3940.06    65.9 3936.48      78  3934.6
    98.1 3928.76   106.2 3927.73   166.6 3912.27   182.7 3904.67   194.8 3905.58
   203.1 3901.69   206.8 3900.56   221.4 3900.17     235 3901.67   250.7 3902.65
   271.1 3900.98   291.2 3903.29   303.3 3902.57   320.3 3899.41   327.2 3900.57
   339.5 3905.85   351.5 3907.67   398.8 3907.04   408.9 3905.73   490.2 3901.71
   533.1 3903.89   564.9    3903   622.3 3904.37   698.5 3902.26     816 3907.84
#Mann= 4 ,-1,0
       0      .1       0   203.1    .045       0     235      .1       0
  299.87     .12       0
#XS Ineff= 2 ,-1
  250.83  285.71 3908.68  357.49     816 3921.22
Permanent Ineff=
       F       F
Bank Sta=203.1,235
XS Rating Curve= 0 ,0
Exp/Cntr(USF)=0,0
Exp/Cntr=0.3,0.1

Type RM Length L Ch R = 1 ,772     ,256.9,269,274.2
XS GIS Cut Line= 4
 2265652.5840372527507.7767941342265684.70352182527242.791046017
2265600.38987469527072.8254399012265458.52881762526641.889021247
#Sta/Elev= 30
       0 3918.22    18.7 3915.09    46.9 3912.58    87.2 3909.97    99.3 3910.01
   135.6 3904.65   178.1 3904.12   204.1    3902     232 3898.44   248.4  3898.5
   274.5 3896.38   304.4 3896.91  309.85 3895.11   322.1 3893.72   334.2 3893.87
   340.1 3894.96   349.1 3896.88   411.6 3896.05   420.5 3896.84   433.9 3899.78
   460.5  3899.3   532.1 3894.59   599.5 3895.98   616.3 3894.75   700.5 3895.91
   763.4 3900.04     789 3903.04   865.2 3905.95   894.2 3911.29   910.3 3912.84
#Mann= 6 ,-1,0
       0      .1       0     240     .12       0  309.85    .045       0
   340.1     .12       0  656.65      .1       0  866.65     .06       0
#XS Ineff= 2 ,-1
  176.08  297.34  3906.7  360.39   910.3 3906.46
Permanent Ineff=
       F       F
Bank Sta=309.85,340.1
XS Rating Curve= 0 ,0
Exp/Cntr(USF)=0,0
Exp/Cntr=0.3,0.1

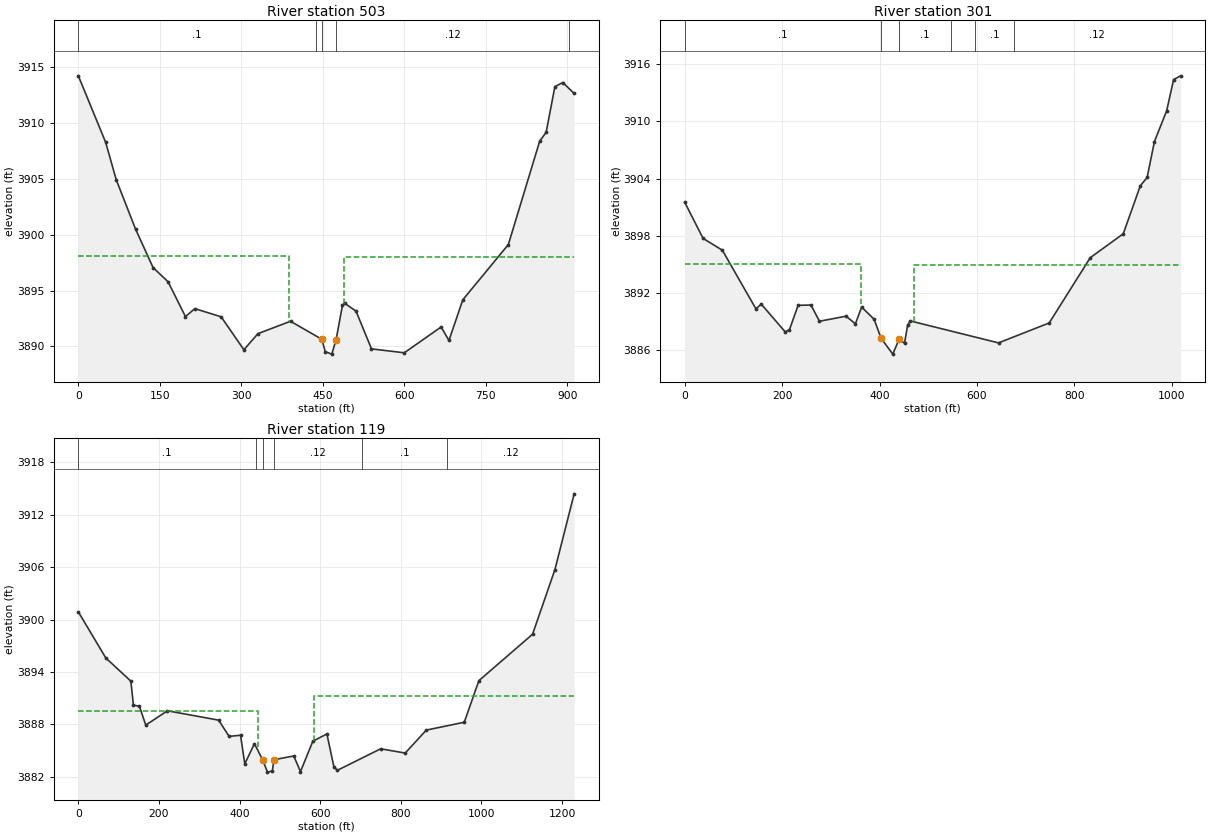
Type RM Length L Ch R = 1 ,503     ,200.9,201.5,198.4
XS GIS Cut Line= 4
2265756.97236221 527481.010556952265858.68406351527300.338455961
2265869.39055838526975.1286741812265585.66844424526722.187732797
#Sta/Elev= 30
       0 3914.21    50.3 3908.26    69.8 3904.91   105.4 3900.49   137.5 3897.06
   165.1 3895.79   197.2 3892.67   214.5 3893.38   262.9 3892.65   304.8  3889.7
   330.6 3891.14   390.6 3892.25   448.2 3890.64   454.6 3889.53   466.6 3889.31
   474.6 3890.61   486.3 3893.69   490.6 3893.85   511.2 3893.16   539.7 3889.78
   600.1 3889.43   667.9 3891.74   682.3 3890.53   707.8 3894.17   791.6 3899.11
   849.4 3908.37   861.2 3909.15   877.3 3913.24   891.9 3913.61   912.8 3912.63
#Mann= 5 ,-1,0
       0      .1       0  437.33     .12       0   448.2    .045       0
   474.6     .12       0  902.72      .1       0
#XS Ineff= 2 , 0
          388.41 3898.07  489.86         3898.03
Permanent Ineff=
       F       F
Bank Sta=448.2,474.6
XS Rating Curve= 0 ,0
Exp/Cntr(USF)=0,0
Exp/Cntr=0.3,0.1

Type RM Length L Ch R = 1 ,301     ,179.7,181.8,182.2
XS GIS Cut Line= 6
2265892.14185999527474.3189976542266000.54512058527361.900801483
2266044.70941194527272.2339069192266054.07759495527062.118945028
2265801.13665357526850.6656712782265620.46455258526720.849420938
#Sta/Elev= 30
       0 3901.51    37.6 3897.73    77.2 3896.49   146.1 3890.34     157 3890.84
     206 3887.94   214.9 3888.14   232.8 3890.71   259.2 3890.74   276.6 3889.04
   331.3 3889.57   350.5 3888.77   363.3 3890.53   388.9 3889.25   403.3 3887.25
   427.3 3885.59   440.1 3887.14   451.4 3886.74   457.9 3888.67   463.4 3889.07
   644.5 3886.77   748.6 3888.86     833 3895.71   900.8 3898.22   935.8 3903.25
   949.8 3904.13   964.8 3907.89   989.9 3911.12  1004.2  3914.4  1018.6 3914.79
#Mann= 6 ,-1,0
       0      .1       0   403.3    .045       0   440.1      .1       0
  546.45     .12       0  596.45      .1       0  676.45     .12       0
#XS Ineff= 2 , 0
             363    3895  471.88          3894.9
Permanent Ineff=
       F       F
Bank Sta=403.3,440.1
XS Rating Curve= 0 ,0
Exp/Cntr(USF)=0,0
Exp/Cntr=0.3,0.1

Type RM Length L Ch R = 1 ,119     ,,,
XS GIS Cut Line= 4
2265914.59680324527479.7175345382266221.70880428527208.129682866
2266234.31414761527084.3681302052265645.30083217526714.229412526
#Sta/Elev= 30
       0 3900.88    68.1 3895.61   130.3 3892.95   136.7 3890.21   151.6 3890.07
   167.3 3887.92     221 3889.56     348 3888.49   374.1 3886.63   402.4 3886.76
   412.9 3883.49   436.8 3885.79   457.2 3883.96   469.2 3882.54   481.3 3882.67
   485.3 3883.96   534.4 3884.39   551.1  3882.6   581.8 3886.08   616.6 3886.91
     634 3883.15   642.7 3882.75     750 3885.21   810.9 3884.72   863.2 3887.35
   957.4 3888.25   993.7 3893.01  1126.8 3898.32  1182.3 3905.72    1230 3914.39
#Mann= 6 ,-1,0
       0      .1       0  439.97     .12       0   457.2    .045       0
   485.3     .12       0  704.37      .1       0  914.37     .12       0
#XS Ineff= 2 , 0
          446.38 3889.51  584.35         3891.21
Permanent Ineff=
       F       F
Bank Sta=457.2,485.3
XS Rating Curve= 0 ,0
Exp/Cntr(USF)=0,0
Exp/Cntr=0.3,0.1
LCMann Table=0

Chan Stop Cuts=-1
Use User Specified Reach Order=0
Composite Channel Slope=5